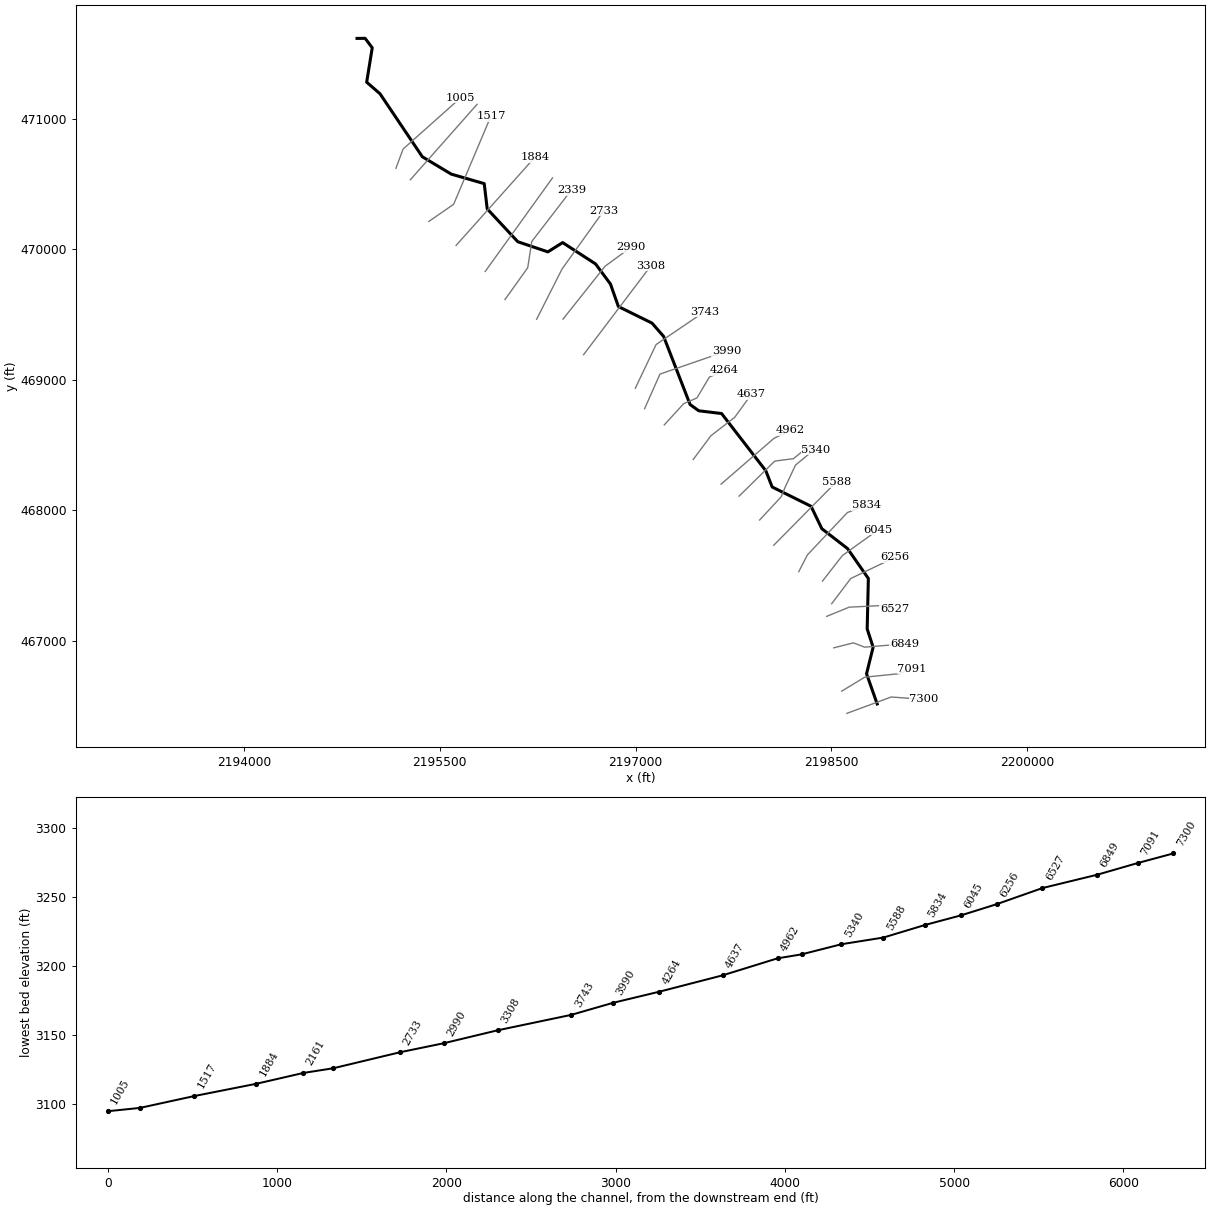
--- DAYRN.prj (project) ---

Proj Title=DAYRN
Current Plan=p01
Default Exp/Contr=0,0
English Units
Geom File=g01
Flow File=f01
Plan File=p01
Background Map Layer=Inundation Boundary (01pct Value_0)
BEGIN DESCRIPTION:
----------MODEL BY WOOD PLC 2021----------
Stream Name: Day Run
Flood Zone: Approximate
Pocahontas County, WV
HEC-RAS Version: RAS 6.1
Vertical Datum: NAVD88
Projection: NAD 1983 StatePlane West Virginia S FIPS 4702 (US Feet)
Terrain: 1-meter LIDAR (FEMA Region III 3DEP collected 2016-2018)
Land Use: 2019 NLCD
Hydrologic Method:
WV SIR2010-5033 regression equations
END DESCRIPTION:
DSS Export Rating Curves= 0
DSS Export Rating Curve Sorted= 0
DSS Export Volume Flow Curves= 0
DXF OffsetX= 0
DXF OffsetY= 0
DXF ScaleX= 0
DXF ScaleY= 0

--- DAYRN.p01 (plan) ---

Plan Title=Floodplain
Program Version=6.10
Short Identifier=Floodplain
Geom File=g01
Flow File=f01
Subcritical Flow
K Sum by GR= 0
Std Step Tol= 0.01
Critical Tol= 0.01
Num of Std Step Trials= 20
Max Error Tol= 0.3
Flow Tol Ratio= 0.001
Split Flow NTrial= 30
Split Flow Tol= 0.02
Split Flow Ratio= 0.02
Log Output Level= 0
Friction Slope Method= 1
Unsteady Friction Slope Method= 2
Unsteady Bridges Friction Slope Method= 1
Parabolic Critical Depth
Global Vel Dist= 0 , 0 , 0
Global Log Level= 0
CheckData=True
Encroach Param=-1 ,0,0, 0
Mapping Interval=1HOUR
Computation Time Step Use Courant=        0
Computation Time Step Use Time Series=    0
Computation Time Step Count To Double=0
Computation Time Step Max Doubling=0
Computation Time Step Max Halving=0
Computation Time Step Residence Courant=0
Run HTab= 0
Run UNet= 0
Run Sediment= 0
Run PostProcess= 0
Run WQNet= 0
Run RASMapper=-1
UNET Theta= 0
UNET Theta Warmup= 0
UNET ZTol= 0
UNET ZSATol= 0
UNET MxIter= 0
UNET Max Iter WO Improvement= 0
UNET MaxInSteps= 0
UNET DtIC= 0
UNET DtMin= 0
UNET MaxCRTS= 0
UNET WFStab= 0
UNET SFStab= 0
UNET WFX= 1
UNET SFX= 1
UNET Gravity=32.174
UNET 1D Methodology=Finite Difference
UNET DSS MLevel= 1
UNET Pardiso=0
UNET DZMax Abort= 0
UNET Use Existing IB Tables= 0
UNET Froude Reduction=False
UNET Froude Limit= 0
UNET Froude Power= 0
UNET D1 Cores= 0
UNET WindReference=Eulerian
UNET WindDragFormulation=Hsu (1988)
UNET D2 Coriolis=0
UNET D2 Cores= 0
UNET D2 Theta= 1
UNET D2 Theta Warmup= 1
UNET D2 Z Tol= 0.01
UNET D2 Volume Tol= 0.01
UNET D2 Max Iterations= 20
UNET D2 Equation= 0
UNET D2 RampUpFraction=0.1
UNET D2 TimeSlices= 1
UNET D2 Turbulence Formulation=Non-Conservative (original)
UNET D2 Eddy Viscosity=0.3
UNET D2 Transverse Eddy Viscosity=0.1
UNET D2 Smagorinsky Mixing=0
UNET D2 BCVolumeCheck=0
UNET D2 Cores=0
UNET D2 SolverType=PARDISO (Direct)
UNET D2 Minimum Iterations= 2147483647
UNET D2 Maximum Iterations= 2147483647
UNET D2 Restart Number= 10
UNET D2 Relaxation Coeff=1.3
UNET D2 SOR Precondition Iterations= 10
UNET D2 ILUT Maximum Fill= 8
UNET D2 ILUT Tolerance=1E-08
UNET D1D2 MaxIter= 0
UNET D1D2 ZTol=0.01
UNET D1D2 QTol=0.1
UNET D1D2 MinQTol=1
Write IC File= 0
Write IC File at Fixed DateTime=0
Write IC File at Sim End=0
Echo Input=False
Echo Parameters=False
Echo Output=False
Write Detailed= 0
HDF Write Warmup=0
HDF Write Time Slices=0
HDF Flush=0
HDF Compression= 1
HDF Chunk Size= 1
HDF Spatial Parts= 1
HDF Use Max Rows=0
HDF Fixed Rows= 1
Calibration Method= 0
Calibration Iterations= 20
Calibration Max Change=0.05
Calibration Tolerance=0.2
Calibration Maximum=1.5
Calibration Minimum=0.5
Calibration Optimization Method= 1
WQ AD Non Conservative
WQ ULTIMATE=-1
WQ Max Comp Step=1HOUR
WQ Output Interval=15MIN
WQ Output Selected Increments= 0
WQ Output face flow=0
WQ Output face velocity=0
WQ Output face area=0
WQ Output face dispersion=0
WQ Output cell volume=0
WQ Output cell surface area=0
WQ Output cell continuity=0
WQ Output cumulative cell continuity=0
WQ Output face conc=0
WQ Output face dconc_dx=0
WQ Output face courant=0
WQ Output face peclet=0
WQ Output face adv mass=0
WQ Output face disp mass=0
WQ Output cell mass=0
WQ Output cell source sink temp=0
WQ Output nsm pathways=0
WQ Output nsm derived pathways=0
WQ Create Restart=0
WQ Fixed Restart=0
WQ System Summary=0
WQ Write To DSS=0
Sorting and Armoring Iterations= 10
XS Update Threshold= 0.02
Bed Roughness Predictor= 0
Hydraulics Update Threshold= 0.02
Energy Slope Method= 1
Volume Change Method= 1
Sediment Retention Method= 0
Sediment TS Multiplier= 1
Warm Up Method= 0
XS Weighting Method= 0
Number of US Weighted Cross Sections= 1
Number of DS Weighted Cross Sections= 1
Upstream XS Weight=0
Main XS Weight=1
Downstream XS Weight=0
Number of DS XS's Weighted with US Boundary= 1
Upstream Boundary Weight= 1
Weight of XSs Associated with US Boundary= 0
Number of US XS's Weighted with DS Boundary= 1
Downstream Boundary Weight= 0.5
Weight of XSs Associated with DS Boundary= 0.5
Percentile Method= 0
Sediment Output Level= 3
Mass or Volume Output= 0
Output Increment Type= 1
Profile and TS Output Increment= 1
Transport Output Increment 1
XS Output Flag= 0
XS Output Increment= 10
Read HDF5 Sediment Hotstart= 0
Sediment Hotstart Type= 0
Write Gradation File= 0
Read Gradation Hotstart= 0
Write HDF5 File= 1
Write Binary Output= 1
Write DSS Sediment File= 0
DSS Sediment Output Type= 1
SV Curve= 0
Specific Gage Flag= 0
Subcell Erosion Methods= 0
Subcell Deposition Methods= 0
Advection Scheme= 1
Matrix Solver= 0
Implicit Weighting Factor= 1
Maximum Outer Loop Convergence Iterations= 5
Convergence Maximum Absolute= 0.001
Convergence RMSE= 0.0001
Grain Fractions Max Abs Error= 0.001
Max Subgrid Regions= 1
Max Subgrid Length Scale= 3.402823E+38
Initial Layer Thickness= 3.402823E+38
Min Layer Thickness= 3.402823E+38
Max Layer Thickness= 3.402823E+38
Number of Layers= 5

--- DAYRN.f01 (steady flow) ---

Flow Title=Flow
Program Version=6.10
Number of Profiles= 6
Profile Names=01pct,10pct,04pct,02pct,0_2pct,01plus
River Rch & RM=DAYRN,Main            ,7300
     611     324     430     517     852     903
River Rch & RM=DAYRN,Main            ,4637
     701     373     494     594     975    1040
Boundary for River Rch & Prof#=DAYRN,Main            , 1
Up Type= 0
Dn Type= 3
Dn Slope=0.0542
Boundary for River Rch & Prof#=DAYRN,Main            , 2
Up Type= 0
Dn Type= 3
Dn Slope=0.0542
Boundary for River Rch & Prof#=DAYRN,Main            , 3
Up Type= 0
Dn Type= 3
Dn Slope=0.0542
Boundary for River Rch & Prof#=DAYRN,Main            , 4
Up Type= 0
Dn Type= 3
Dn Slope=0.0542
Boundary for River Rch & Prof#=DAYRN,Main            , 5
Up Type= 0
Dn Type= 3
Dn Slope=0.0542
Boundary for River Rch & Prof#=DAYRN,Main            , 6
Up Type= 0
Dn Type= 3
Dn Slope=0.0542
DSS Import GetInterval= 0
DSS Import GetPeak= 0
DSS Import FillOption= 0

--- DAYRN.g01 (geometry) ---

Geom Title=Geometry
Program Version=6.10

River Reach=DAYRN           ,Main
Reach XY= 30
2198851.34500001 466514.200444462198769.86067988466745.371461779
2198820.29950003466948.9679444732198774.75200002467088.733444467
     2198783.737467475.593444467     2198624.154467704.747444466
2198427.36600001 467856.896444472198344.51063409468028.914339507
2198046.57399999468176.6064444482197998.19500004468300.646444485
2197659.18699999468739.2404444662197484.30232467468760.521421179
2197417.73308094 468808.511856632197214.89600004469330.479444474
2197126.00194226469432.3593251712196868.54531722469559.000799015
 2196807.6713875469731.6355081652196693.19401322469885.927017331
2196441.12050547470049.3189063152196328.19401319469978.149239555
2196097.73202853470055.7321144942195863.19401322470307.593684018
2195840.47322118470501.0302625312195587.96635154470573.805027305
2195366.16800003470706.8454444712195041.82700004471189.657444462
2194939.54096114471278.4152529052194982.23200004471541.842444479
2194927.78682056471614.3825576612194865.87316094471613.799936488

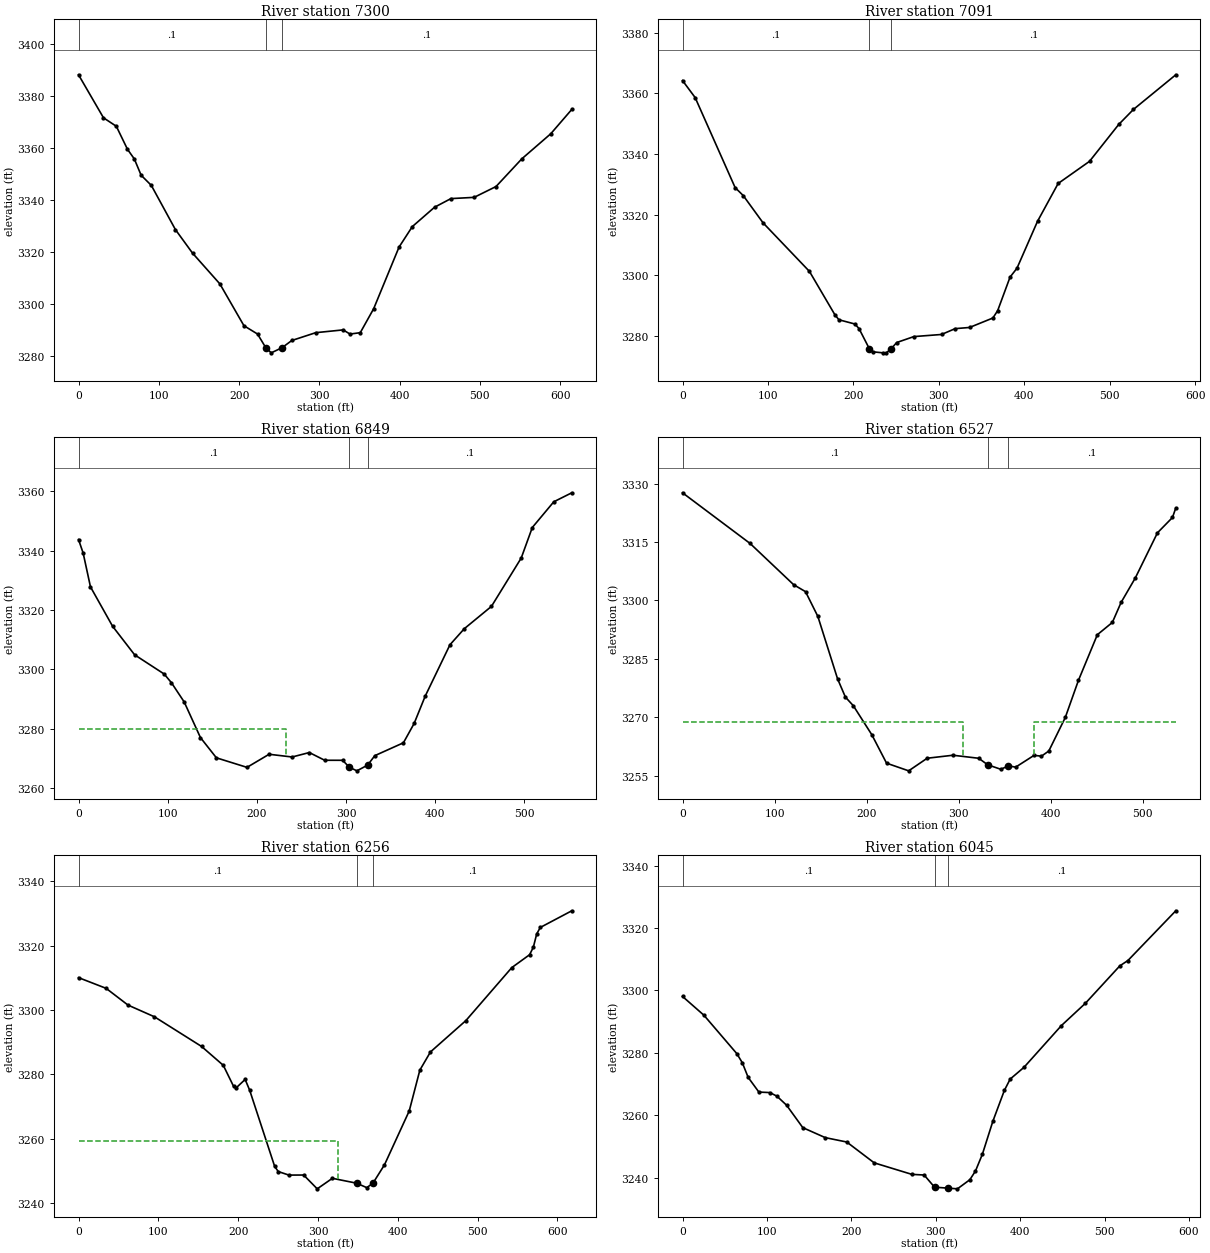
Type RM Length L Ch R = 1 ,7300    ,211.4,209,202.3
XS GIS Cut Line= 3
2198618.98956019466441.8681115032198958.76632296466567.468045756
2199210.36313994466549.108591299
#Sta/Elev= 30
       0 3388.33    31.1 3371.77    47.1 3368.51      61 3359.64    69.5 3355.95
      78 3349.67    90.7 3345.75   120.7 3328.75     142  3319.7   176.1 3307.84
   206.1 3291.74     223 3288.55   233.2 3283.33   240.1 3281.31   253.5 3283.28
   265.7 3286.06   295.5 3289.07   329.6 3290.14   338.2 3288.54     351 3289.07
   367.7 3298.31   399.3 3322.02   415.8 3329.89   443.5 3337.35   463.9 3340.67
   492.8 3341.15   520.1 3345.32   552.2 3355.97   588.3 3365.63   614.5    3375
#Mann= 3 ,-1,0
       0      .1       0   233.2    .045       0   253.5      .1       0
Bank Sta=233.2,253.5
XS Rating Curve= 0 ,0
Exp/Cntr=0.3,0.1

Type RM Length L Ch R = 1 ,7091    ,241.1,242.2,238.5
XS GIS Cut Line= 4
2198579.50399159466612.2341435792198756.25469086466719.168316639
2199016.07821879 466745.680921532199118.59362437 466784.56607537
#Sta/Elev= 30
       0 3364.23    14.8 3358.61    61.6 3328.91    71.1 3326.28    94.3 3317.28
   148.6 3301.26   178.4 3286.94   183.1 3285.31   201.8 3283.91   206.6 3282.41
   218.6 3275.81   222.6 3274.74   234.6  3274.4   238.7 3274.41   244.5 3275.82
   250.7  3277.8   270.8 3279.76   303.2 3280.46   319.1 3282.38     336 3282.77
   363.3 3285.89   368.9 3288.32   383.4 3299.38   391.5 3302.31   415.6 3317.82
   439.7 3330.27   476.4 3337.57   510.6 3349.74   527.8 3354.69   577.4 3366.13
#Mann= 3 ,-1,0
       0      .1       0   218.6    .045       0   244.5      .1       0
Bank Sta=218.6,244.5
XS Rating Curve= 0 ,0
Exp/Cntr(USF)=0,0
Exp/Cntr=0.3,0.1

Type RM Length L Ch R = 1 ,6849    ,322.2,322.4,320.9
XS GIS Cut Line= 4
2198519.15767938466944.0750328322198669.60810685466982.204415136
2198754.49755561466949.3207065692199060.31119348466974.105532213
#Sta/Elev= 30
       0  3343.7     5.2 3339.13    13.4 3327.76    38.2  3314.5    62.9 3304.89
      96 3298.43   104.2 3295.49   118.5 3289.01   136.7 3277.03   154.6 3270.21
   188.9    3267   213.7 3271.41   239.5 3270.49   258.8 3271.99     276 3269.39
   296.1 3269.38   303.63267.067   312.1 3265.83   324.2 3267.76   332.2 3270.94
   364.3 3275.27   376.3 3281.77   388.7 3290.96   416.5 3308.28   432.5 3313.66
     463 3321.19   496.4 3337.47   508.8 3347.74   532.9  3356.4   553.1 3359.43
#Mann= 3 ,-1,0
       0      .1       0   303.6    .045       0   324.2      .1       0
#XS Ineff= 2 , 0
          232.56 3279.92
Permanent Ineff=
       F       F
Bank Sta=303.6,324.2
XS Rating Curve= 0 ,0
Exp/Cntr=0.3,0.1

Type RM Length L Ch R = 1 ,6527    ,264.7,271.1,277.1
XS GIS Cut Line= 4
2198464.51226975467185.1338485242198636.83597662467255.722137751
2198870.33782491467267.2079572052198983.67898278467243.857033852
#Sta/Elev= 30
       0 3327.68    73.4 3314.65   120.7 3304.05   133.6 3302.26     147 3295.89
   168.4 3279.85   176.9 3275.16   185.5 3272.94   205.6 3265.48   221.6 3258.17
   245.6  3256.2   265.7 3259.44   293.7 3260.21   321.7 3259.43   331.4 3257.76
   345.8 3256.59   353.8 3257.49   361.8 3257.15   381.8 3260.18   389.8 3259.97
   397.8  3261.3   415.7 3269.92     430 3279.47   450.5 3291.19   466.8 3294.35
   476.3 3299.49   491.8 3305.81   515.8 3317.39   532.1 3321.33   535.7 3323.77
#Mann= 3 ,-1,0
       0      .1       0   331.4    .045       0   353.8      .1       0
#XS Ineff= 2 , 0
          304.98 3268.85  381.59         3268.73
Permanent Ineff=
       F       F
Bank Sta=331.4,353.8
XS Rating Curve= 0 ,0
Exp/Cntr(USF)=0,0
Exp/Cntr=0.3,0.1

Type RM Length L Ch R = 1 ,6256    ,206.8,210.6,212.6
XS GIS Cut Line= 3
2198502.83949955467282.0896321212198648.57812804467475.084359665
 2198987.8219921467637.793907467
#Sta/Elev= 30
       0 3310.08    34.6 3306.75      62 3301.55    95.1 3297.92   154.2  3288.7
   181.4 3282.84   194.3 3276.31   197.4 3275.81   208.8 3278.46   214.5 3275.08
   245.8 3251.43   250.3 3249.85   263.6 3248.75   282.1 3248.77   299.1 3244.48
   318.1 3247.75   348.4 3246.24   361.2 3244.85     369 3246.26   383.4 3251.95
   414.4 3268.68   427.7 3281.35     441    3287   485.4 3296.74   542.9 3313.19
   565.2 3317.19   569.9 3319.52   574.1 3323.63   578.6 3325.66   618.1 3330.84
#Mann= 3 ,0,0
       0      .1       0   348.4    .045       0     369      .1       0
#XS Ineff= 2 , 0
          324.59 3259.43
Permanent Ineff=
       F       F
Bank Sta=348.4,369
XS Rating Curve= 0 ,0
Exp/Cntr=0.3,0.1

Type RM Length L Ch R = 1 ,6045    ,208.4,211.5,213.8
XS GIS Cut Line= 3
2198432.56936535467455.7851397862198584.77809129467651.097221744
2198858.21500603467847.756283578
#Sta/Elev= 30
       0 3298.07    25.4 3292.04    64.4 3279.72    70.9 3276.79    77.8 3272.11
    90.5 3267.41   103.5 3267.25   111.9 3266.09   123.3  3263.2   142.5 3256.01
   169.1 3252.81   194.6  3251.4   227.1 3244.72   271.7 3241.03   286.3 3240.82
   298.63236.914   314.6 3236.62   325.7 3236.39   340.4 3239.31   347.1 3242.11
   355.3 3247.51   367.6 3257.99   381.3 3267.94   388.2 3271.58   404.5 3275.33
   448.9 3288.73   477.3 3295.87   518.1 3307.87   527.7 3309.59   584.4 3325.53
#Mann= 3 ,0,0
       0      .1       0   298.6    .045       0   314.6      .1       0
Bank Sta=298.6,314.6
XS Rating Curve= 0 ,0
Exp/Cntr(USF)=0,0
Exp/Cntr=0.3,0.1

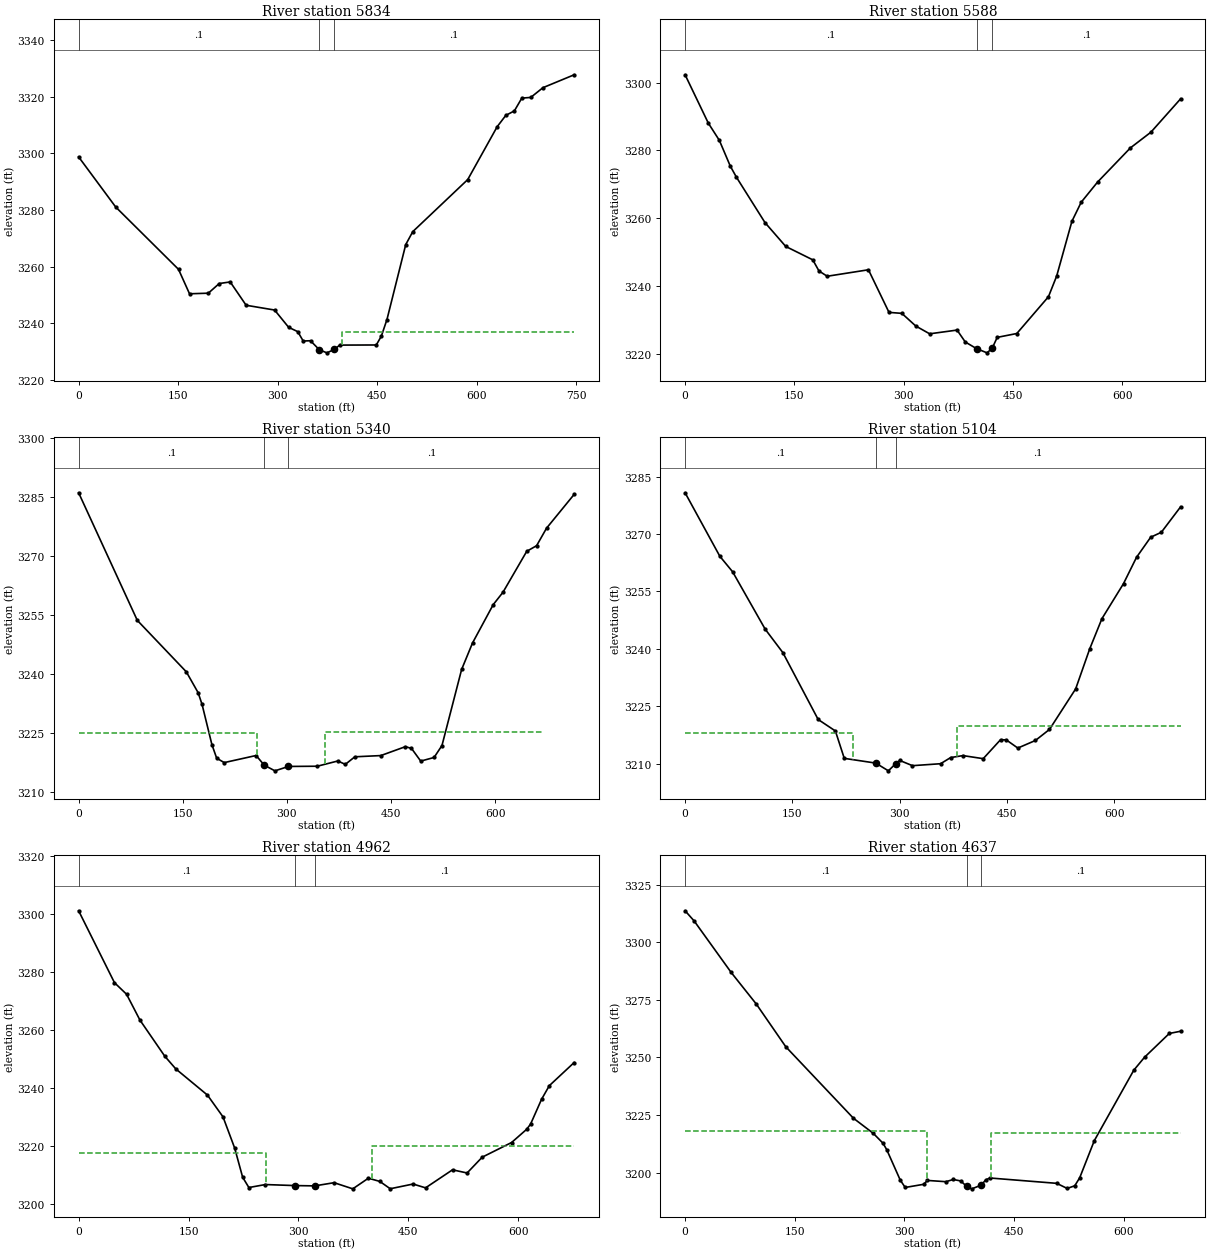
Type RM Length L Ch R = 1 ,5834    ,247,246.1,244.5
XS GIS Cut Line= 4
2198250.55120067467527.672400826 2198316.8817983467656.411097497
2198623.04832168467980.6659945412198767.91789941468038.385198607
#Sta/Elev= 30
       0 3298.77    55.8 3281.06   150.5    3259   167.1 3250.35   195.4 3250.56
   211.9 3253.98   228.4 3254.54   252.4 3246.29   295.3  3244.6   316.4  3238.5
   330.2 3236.95   338.4 3233.64   349.4 3233.74   362.7 3230.55   374.1 3229.46
   385.4 3230.68   393.4  3232.2   448.5 3232.24   456.1 3235.34   464.6 3241.24
   492.9 3267.76   503.5 3272.33   586.3 3290.75   630.7 3309.46   643.7 3313.46
   656.6 3315.05   667.8 3319.56   681.3 3319.81   699.6 3323.25   746.7 3327.82
#Mann= 3 ,0,0
       0      .1       0   362.7    .045       0   385.4      .1       0
#XS Ineff= 2 , 0
                          396.23         3236.86
Permanent Ineff=
       F       F
Bank Sta=362.7,385.4
XS Rating Curve= 0 ,0
Exp/Cntr=0.3,0.1

Type RM Length L Ch R = 1 ,5588    ,239.9,247.8,253.8
XS GIS Cut Line= 2
2198059.15176261467730.4616166742198537.07326894468214.235223074
#Sta/Elev= 30
       0 3302.31    31.9 3288.04      47 3282.98      62 3275.39    70.5 3272.09
   109.6 3258.74   138.1  3251.7   175.2 3247.75   183.7 3244.47     195 3242.91
   251.6 3244.82   279.8 3232.26   297.4 3231.97   316.6 3228.23   335.6 3225.94
   373.2 3227.04   384.5 3223.52   399.9 3221.58   414.3 3220.33   421.3 3221.64
   428.3 3224.89   455.2 3226.03   498.6 3236.87   509.9 3242.98   530.8 3259.11
   543.6 3264.75   566.1  3270.7   611.1 3280.76   639.2 3285.38     680 3295.23
#Mann= 3 ,-1,0
       0      .1       0   399.9    .045       0   421.3      .1       0
Bank Sta=399.9,421.3
XS Rating Curve= 0 ,0
Exp/Cntr(USF)=0,0
Exp/Cntr=0.3,0.1

Type RM Length L Ch R = 1 ,5340    ,244.4,235.4,225.9
XS GIS Cut Line= 6
 2197950.6627269 467923.463415082198116.34401297468101.991418366
2198148.09187185468179.7423115972198225.43636483 468344.05845513
2198376.12209499 468468.871541892198383.12839979468463.471599174
#Sta/Elev= 30
       0 3286.01    84.5 3253.65   155.1  3240.6   172.1 3235.31   177.8 3232.32
   191.9 3222.17   198.8  3218.7   209.7 3217.58   255.6 3219.38   267.4 3216.92
   282.7 3215.49   302.23216.603   343.7 3216.66   373.3 3217.99   384.1 3217.13
   397.8 3219.05   435.2 3219.36   470.6 3221.62   479.4 3221.18   492.7 3217.96
   511.9 3218.88   523.3 3221.91   551.6  3241.2   567.3 3247.92   597.1 3257.64
   611.2 3260.79   645.4 3271.17   659.6 3272.59   673.9 3277.03   713.7 3285.61
#Mann= 3 ,-1,0
       0      .1       0   267.4    .045       0   302.2      .1       0
#XS Ineff= 2 ,-1
       0  256.74 3225.09  355.28  668.79 3225.43
Permanent Ineff=
       F       F
Bank Sta=267.4,302.2
XS Rating Curve= 0 ,0
Exp/Cntr=0.3,0.1

Type RM Length L Ch R = 1 ,5104    ,144.4,142.4,142.1
XS GIS Cut Line= 4
2197793.49941961 468106.641713752198066.26284441468375.040923757
2198210.28193271468393.5888366442198337.93521552468498.329991769
#Sta/Elev= 30
       0 3280.77    48.6 3264.18    66.4 3260.15     112 3245.14   136.6 3239.05
   186.1 3221.55   210.2 3218.55   222.6  3211.4   266.7 3210.16   284.3 3208.14
   294.5 3210.02   300.2 3210.85     318 3209.49   357.3    3210   371.4 3211.61
   388.6 3212.12   416.9 3211.32   441.1 3216.26   449.1 3216.23   465.3 3214.09
   489.9 3216.07   509.6 3218.96   546.2 3229.55   565.9 3240.03   582.9 3247.88
   613.1 3257.04   631.3 3263.91   651.1 3269.16     666 3270.45     693 3277.11
#Mann= 3 ,-1,0
       0      .1       0   266.7    .045       0   294.5      .1       0
#XS Ineff= 2 , 0
          234.37 3218.13  379.87         3219.91
Permanent Ineff=
       F       F
Bank Sta=266.7,294.5
XS Rating Curve= 0 ,0
Exp/Cntr(USF)=0,0
Exp/Cntr=0.3,0.1

Type RM Length L Ch R = 1 ,4962    ,327,324.8,324.5
XS GIS Cut Line= 3
2197655.22773709468198.3891785472198061.49821387 468550.10444969
2198186.74753503 468610.04139236
#Sta/Elev= 30
       0 3301.24    48.9 3276.42    65.4 3272.43    83.7 3263.49   117.6 3251.02
   132.6 3246.65   175.8 3237.61     197  3230.1   212.9 3219.34   223.8 3209.26
   232.3  3205.7   254.8 3206.73   294.7 3206.38   322.1 3206.27   348.6 3207.37
   374.1 3205.25   395.4 3208.92     411 3207.81   425.2 3205.28   456.4 3206.91
   473.4 3205.59   510.2 3211.82   530.1 3210.72   550.7 3216.18   590.8 3221.24
   611.3 3225.79   616.7 3227.59   631.7 3236.16   642.3 3240.87   676.2 3248.86
#Mann= 3 ,-1,0
       0      .1       0   294.7    .045       0   322.1      .1       0
#XS Ineff= 2 , 0
          255.27  3217.7     400            3220
Permanent Ineff=
       F       F
Bank Sta=294.7,322.1
XS Rating Curve= 0 ,0
Exp/Cntr=0.3,0.1

Type RM Length L Ch R = 1 ,4637    ,376.3,373,367.3
XS GIS Cut Line= 4
2197441.83211712468387.2601328362197577.27674966  468568.9541521
2197759.80696299468710.6394631132197889.28315674468889.072342622
#Sta/Elev= 30
       0 3313.61    12.4 3309.19    63.1 3286.82    97.4 3273.14   137.8 3254.58
   230.3 3223.57   257.4 3217.03   270.8 3212.72   275.9 3209.92   294.4 3196.71
   301.2 3193.51   326.5 3194.88   331.6 3196.56   356.9 3196.01     367 3196.97
   377.1 3196.34   385.33193.992   392.3 3192.91   405.23194.516   411.3 3196.78
     417 3197.62   508.5  3195.3   522.8 3193.09   533.2 3194.23     540 3197.73
     560 3213.85     614 3244.41   628.7 3250.03   662.6 3260.36   678.1 3261.32
#Mann= 3 ,-1,0
       0      .1       0   385.3    .045       0   405.2      .1       0
#XS Ineff= 2 , 0
          331.02    3218  419.13         3217.23
Permanent Ineff=
       F       F
Bank Sta=385.3,405.2
XS Rating Curve= 0 ,0
Exp/Cntr(USF)=0,0
Exp/Cntr=0.3,0.1

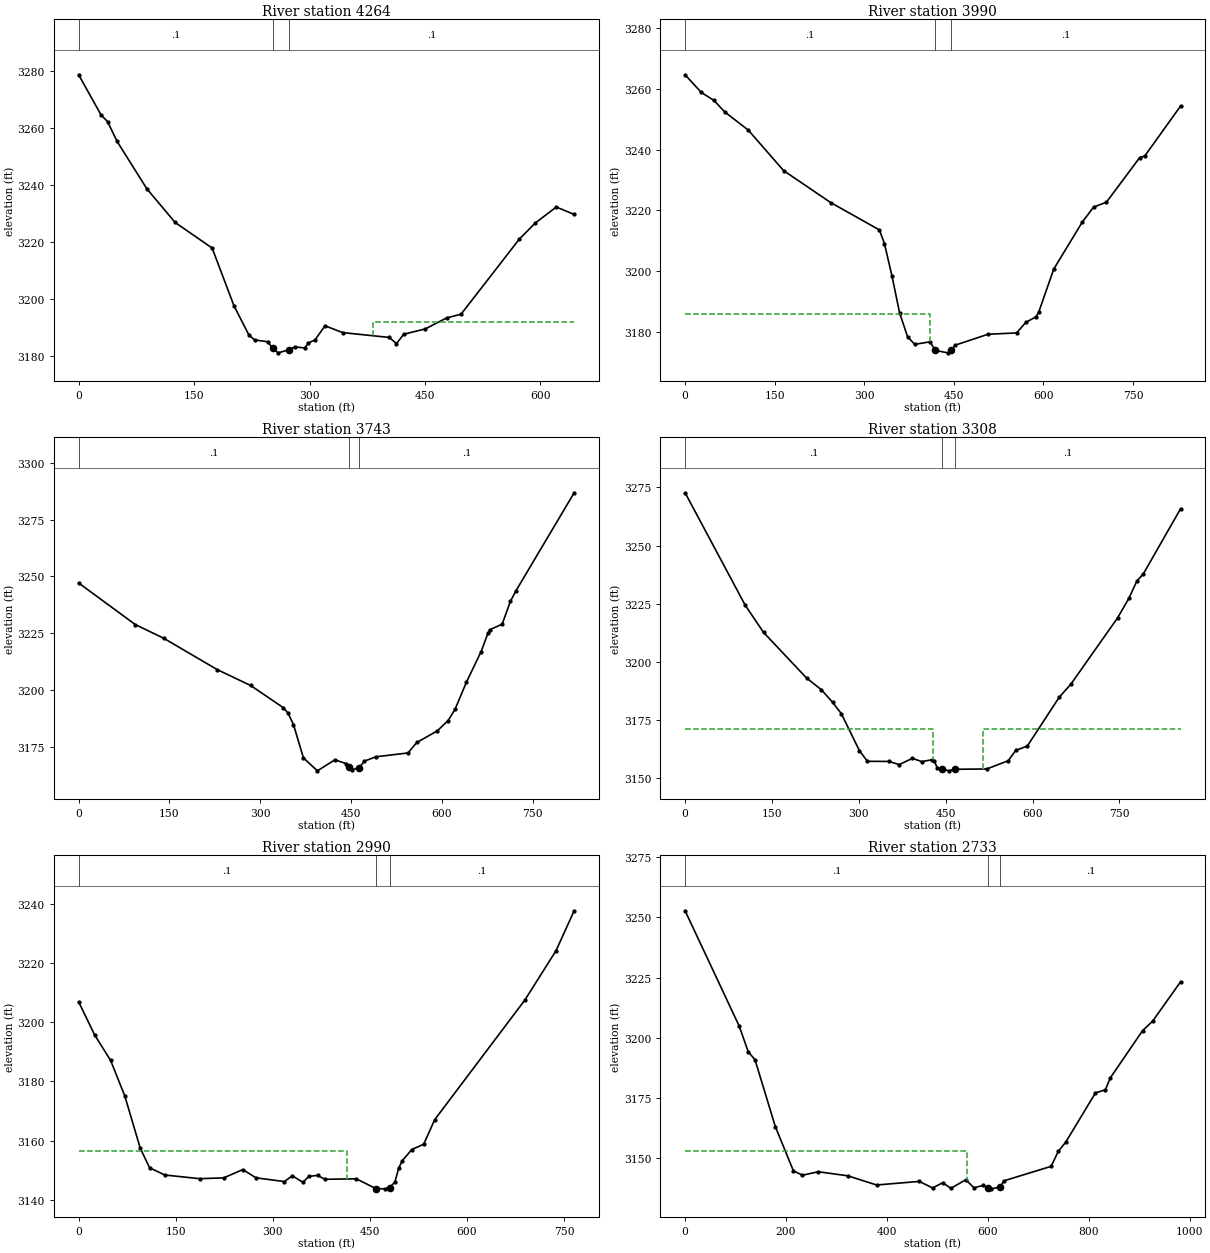
Type RM Length L Ch R = 1 ,4264    ,274.6,273.7,272.1
XS GIS Cut Line= 5
2197219.77672796468652.3980843272197369.42367059468815.572667805
2197470.10152464468858.6201688882197565.70799513469018.920496918
2197681.45953544469069.534843688
#Sta/Elev= 30
       0 3278.55    29.1 3264.49    37.6 3262.14    49.9 3255.24    88.6 3238.61
   125.4 3226.78   173.5 3217.81   201.8  3197.6   221.4 3187.26   228.7 3185.62
   245.8 3184.97   252.2 3182.64   259.2 3181.09   273.5 3182.19     281 3183.16
     294 3182.81   298.4 3184.54   307.1  3185.6   320.1 3190.58     343 3188.19
   403.7 3186.48     413 3184.31   422.4  3187.6   450.3 3189.47   478.3 3193.34
   496.9 3194.63   572.6 3220.94   593.1 3226.53   620.6  3232.2   643.9  3229.6
#Mann= 3 ,-1,0
       0      .1       0   252.2    .045       0   273.5      .1       0
#XS Ineff= 2 , 0
                           382.8         3192.03
Permanent Ineff=
       F       F
Bank Sta=252.2,273.5
XS Rating Curve= 0 ,0
Exp/Cntr=0.3,0.1

Type RM Length L Ch R = 1 ,3990    ,243.1,247,251.4
XS GIS Cut Line= 3
2197069.15526399468776.5338192262197187.04455231469041.655035814
  2197696.909055 469217.71940406
#Sta/Elev= 30
       0 3264.65      27 3258.85    48.2 3256.22    66.5 3252.39   105.8 3246.41
   164.9 3233.07   243.7 3222.54   325.3 3213.52   333.7 3209.04   346.4 3198.28
   359.1 3186.18   372.4 3178.34   384.4  3175.8   409.8 3176.64   419.13173.805
   439.5 3173.01   445.73173.905   452.2 3175.54   507.2 3179.14   554.9 3179.57
   570.6 3183.07   587.6  3184.9   591.8 3186.32   617.2 3200.62     665 3216.13
   683.9 3221.05   705.4 3222.66   761.1 3237.37   769.5 3237.88   829.6 3254.37
#Mann= 3 ,-1,0
       0      .1       0   419.1    .045       0   445.7      .1       0
#XS Ineff= 2 , 0
          409.67 3185.94
Permanent Ineff=
       F       F
Bank Sta=419.1,445.7
XS Rating Curve= 0 ,0
Exp/Cntr(USF)=0,0
Exp/Cntr=0.3,0.1

Type RM Length L Ch R = 1 ,3743    ,430.8,435.3,440.3
XS GIS Cut Line= 3
2196997.76297235468932.6870914152197157.27772239469268.044745673
2197527.35965094469519.182302135
#Sta/Elev= 30
       0  3247.1    93.6 3228.77   140.3 3222.77   229.1 3208.89     284 3201.93
   338.4 3192.08     346 3189.71   354.9 3184.67   371.4 3169.97   394.4 3164.28
   423.2 3169.13   442.5 3167.42   446.3 3166.05     452 3164.78   463.5 3165.72
   472.2 3168.57   490.9 3170.47   544.2 3172.17   558.6 3176.78   592.4 3181.88
   610.4 3186.45   621.9 3191.47   640.7 3203.42   664.9 3216.88   676.6 3225.25
   679.5 3226.53   699.7 3228.96   713.2 3238.97   722.4 3243.65   818.6 3286.87
#Mann= 3 ,0,0
       0      .1       0   446.3    .045       0   463.5      .1       0
Bank Sta=446.3,463.5
XS Rating Curve= 0 ,0
Exp/Cntr(USF)=0,0
Exp/Cntr=0.3,0.1

Type RM Length L Ch R = 1 ,3308    ,318.6,318.6,317.6
XS GIS Cut Line= 2
2196601.51299946469190.0518451062197117.95347269469872.395475531
#Sta/Elev= 30
       0 3272.68   103.8 3224.31   135.5 3212.61   209.7 3193.01   235.4 3187.94
   254.7 3182.55   269.7  3177.7   301.1  3161.7   314.9 3157.17   352.5 3157.11
   369.6 3155.74   392.5 3158.45   408.7 3157.03   426.7 3157.87   430.3 3157.34
   435.3  3154.4   443.9 3153.98   455.1 3153.07   465.4 3153.74     521 3153.88
   558.1 3157.43   570.8 3161.83   590.9 3163.72     646 3184.72   666.1 3190.33
   746.8 3218.87   766.4  3227.3   779.9  3234.6   791.5 3237.89   855.7 3265.86
#Mann= 3 ,-1,0
       0      .1       0   443.9    .045       0   465.4      .1       0
#XS Ineff= 2 , 0
           428.8 3171.11  514.61         3171.07
Permanent Ineff=
       F       F
Bank Sta=443.9,465.4
XS Rating Curve= 0 ,0
Exp/Cntr(USF)=0,0
Exp/Cntr=0.3,0.1

Type RM Length L Ch R = 1 ,2990    ,255.4,256.1,256.7
XS GIS Cut Line= 3
2196443.87726977469462.6085054782196766.48726466469868.365406269
2196966.03983882470014.703960652
#Sta/Elev= 30
       0 3206.91    24.8 3195.69    49.3 3187.14    71.2 3175.18    95.3 3157.38
   109.7 3150.81     133 3148.37   187.3 3147.12   224.1  3147.4   253.7 3150.19
   274.1 3147.41     318 3146.15   330.3 3148.12   346.5  3145.9   355.9 3147.91
   369.3 3148.22   380.7 3146.92   429.1 3147.08   459.23143.791   473.4 3143.69
   480.53144.135   488.8    3146   494.5 3150.66   500.2 3153.21   514.7 3156.94
   533.3 3158.79   550.2 3167.05   689.9  3207.6   737.7 3224.17   765.8 3237.68
#Mann= 3 ,-1,0
       0      .1       0   459.2    .045       0   480.5      .1       0
#XS Ineff= 2 , 0
          415.01 3156.49
Permanent Ineff=
       F       F
Bank Sta=459.2,480.5
XS Rating Curve= 0 ,0
Exp/Cntr(USF)=0,0
Exp/Cntr=0.3,0.1

Type RM Length L Ch R = 1 ,2733    ,386,394.8,399.1
XS GIS Cut Line= 3
2196241.73391987469461.5276313462196436.06061526469845.761426649
2196757.03813879470294.454711345
#Sta/Elev= 30
       0 3252.77   107.2 3204.87   125.1  3194.2   138.6 3190.85   178.9 3163.05
   214.8 3144.66   232.7 3142.88   264.1 3144.32   322.3 3142.64   379.6 3138.82
   464.3 3140.31   490.5 3137.59   510.5 3139.74     527 3137.44   556.4 3141.01
   572.5 3137.67   590.8 3138.62   601.23137.515   606.9 3137.22   625.2 3138.03
   631.5 3140.52   725.6 3146.57   739.9 3152.85   754.5 3156.61   813.5 3177.11
   833.1 3178.36     843 3183.37   906.9 3202.97   926.6 3206.86   982.3  3223.3
#Mann= 3 ,0,0
       0      .1       0   601.2    .045       0   625.2      .1       0
#XS Ineff= 2 , 0
          558.08 3152.84
Permanent Ineff=
       F       F
Bank Sta=601.2,625.2
XS Rating Curve= 0 ,0
Exp/Cntr(USF)=0,0
Exp/Cntr=0.3,0.1

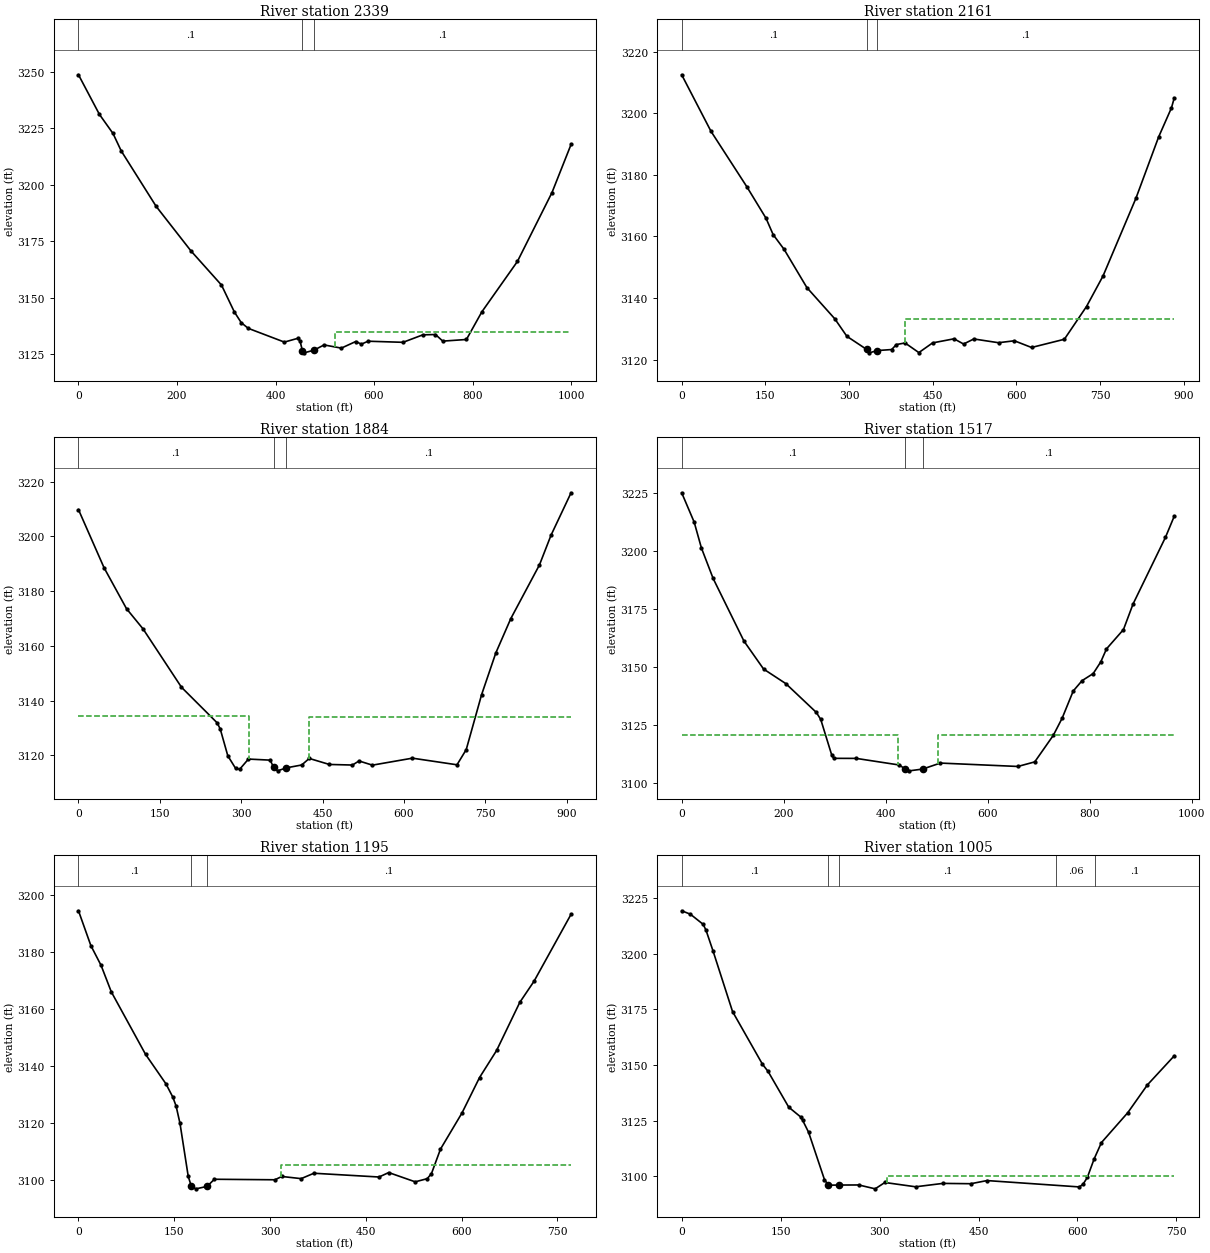
Type RM Length L Ch R = 1 ,2339    ,184.4,177.7,169.5
XS GIS Cut Line= 4
2195999.44509026469612.8373102322196173.37581959469856.340331286
2196205.00214763470058.1168672122196507.76468551470451.465757493
#Sta/Elev= 30
       0 3248.75    42.5  3231.2    70.1 3222.75    86.8 3215.01   157.7 3190.46
   228.4 3170.72   290.3 3155.62   316.4 3143.71   330.4 3138.97   344.6 3136.45
   417.9 3130.36   445.8 3132.06   449.9 3130.68   454.63126.535     458  3125.6
   477.8 3126.76   498.5  3129.1   533.6 3127.69   562.9 3130.62   574.3 3129.44
   587.8 3130.75   658.8 3130.26     699 3133.57   724.7 3133.71   739.5 3130.79
   787.5 3131.51   818.8 3143.75     891 3166.07   961.2 3196.59   999.9 3217.89
#Mann= 3 ,-1,0
       0      .1       0   454.6    .045       0   477.8      .1       0
#XS Ineff= 2 , 0
                          519.88         3134.73
Permanent Ineff=
       F       F
Bank Sta=454.6,477.8
XS Rating Curve= 0 ,0
Exp/Cntr(USF)=0,0
Exp/Cntr=0.3,0.1

Type RM Length L Ch R = 1 ,2161    ,277.3,276.8,273.6
XS GIS Cut Line= 2
2195847.96871659469828.1226364012196363.47953317470544.848965256
#Sta/Elev= 30
       0 3212.56    52.5 3194.19   116.8 3176.15   151.1 3165.94   163.9 3160.61
   183.6  3155.8   224.4 3143.38   274.4 3133.24   296.1 3127.54   331.4  3123.3
   336.2 3122.17   350.83122.915   376.3 3123.24   384.9 3124.87   400.4 3125.38
   425.1 3122.25   449.7  3125.4   488.1 3126.73   505.3 3125.04   523.6 3126.68
   567.9 3125.46   596.3 3126.09   627.1 3123.91   685.9 3126.58   725.6 3137.23
   755.2 3147.15   814.3 3172.47   854.9 3192.36   877.9 3201.82   882.9 3205.05
#Mann= 3 ,-1,0
       0      .1       0   331.4    .045       0   350.8      .1       0
#XS Ineff= 2 , 0
                          400.89         3133.03
Permanent Ineff=
       F       F
Bank Sta=331.4,350.8
XS Rating Curve= 0 ,0
Exp/Cntr(USF)=0,0
Exp/Cntr=0.3,0.1

Type RM Length L Ch R = 1 ,1884    ,354.5,367,371.5
XS GIS Cut Line= 2
2195624.82505787470027.5952032362196229.56882445470704.587118912
#Sta/Elev= 30
       0 3209.77    47.1 3188.56    88.5 3173.59   119.1 3166.17   189.8 3144.89
   255.6 3131.88   261.3 3129.61   275.2 3119.84   289.6 3115.24   297.1 3114.93
   313.2 3118.65   353.3 3118.26   359.63115.633   366.8 3114.35   383.3 3115.45
   411.4 3116.49   425.3 3118.88   462.4 3116.68   504.9 3116.47     517 3117.96
   541.7 3116.43   615.4 3118.98   697.6 3116.56   714.6 3122.11   742.9 3142.16
   769.1 3157.41   796.7 3169.95   849.6  3189.6     871 3200.48   907.8 3215.93
#Mann= 3 ,-1,0
       0      .1       0   359.6    .045       0   383.3      .1       0
#XS Ineff= 2 , 0
          313.98  3134.4  425.16         3134.17
Permanent Ineff=
       F       F
Bank Sta=359.6,383.3
XS Rating Curve= 0 ,0
Exp/Cntr(USF)=0,0
Exp/Cntr=0.3,0.1

Type RM Length L Ch R = 1 ,1517    ,327.5,321.6,316.3
XS GIS Cut Line= 3
2195416.00725745470211.4955383282195605.99313102470342.612549664
2195892.30987007471019.604465342
#Sta/Elev= 30
       0 3224.98    24.5 3212.36    38.7 3201.24    61.7 3188.13   122.1 3161.22
   160.6  3149.2   204.3 3142.92     264 3130.56   272.7 3127.52   294.4  3112.1
   298.6 3110.81   342.2 3110.79   426.7 3107.95   437.7  3106.3   446.4 3105.44
   472.4  3106.2   507.2 3108.78   659.2 3107.32   692.3 3109.29   728.7  3120.7
   746.1  3128.1   767.8 3139.77   785.2 3144.23   806.9 3147.25   821.8 3152.28
     833 3157.87   866.3 3166.18   885.1 3177.17   948.7 3205.86   965.9 3214.92
#Mann= 3 ,-1,0
       0      .1       0   437.7    .045       0   472.4      .1       0
#XS Ineff= 2 , 0
           423.3 3120.67  502.94         3120.88
Permanent Ineff=
       F       F
Bank Sta=437.7,472.4
XS Rating Curve= 0 ,0
Exp/Cntr(USF)=0,0
Exp/Cntr=0.3,0.1

Type RM Length L Ch R = 1 ,1195    ,192.6,190.2,188.3
XS GIS Cut Line= 2
2195274.28774185470530.6563895882195785.37650033471108.641582419
#Sta/Elev= 30
       0 3194.37    19.4 3182.15    35.4 3175.21    51.4 3165.93   105.1 3143.99
   136.9 3133.69   147.8 3128.99   152.9 3125.87     159 3119.78   171.9 3101.19
  176.86 3097.67     184 3096.83   201.5 3097.69   212.8 3100.19   307.7 3100.01
   318.4 3101.17   348.8 3100.41   368.7  3102.3   470.7 3100.98   485.9 3102.54
   527.4 3099.29   546.3  3100.4   552.9 3102.21     567 3110.77   600.7 3123.46
   628.1 3135.85   654.9 3145.37   691.2 3162.24   713.5 3169.65   771.5 3193.14
#Mann= 3 ,-1,0
       0      .1       0  176.86    .045       0   201.5      .1       0
#XS Ineff= 2 , 0
                          317.86         3105.09
Permanent Ineff=
       F       F
Bank Sta=176.86,201.5
XS Rating Curve= 0 ,0
Exp/Cntr(USF)=0,0
Exp/Cntr=0.3,0.1

Type RM Length L Ch R = 1 ,1005    ,245.8,246.4,246.3
XS GIS Cut Line= 3
 2195163.5590001470618.5250455282195218.56273503470765.697201132
2195658.59261441471158.156282743
#Sta/Elev= 30
       0 3219.24    13.2  3217.7    32.7 3213.12      37 3210.41    47.5 3201.22
    77.1    3174   122.4 3150.38   130.9 3147.15   162.3 3131.08   180.6 3126.64
   183.4 3125.17   192.4 3119.81   216.4  3098.6   222.4 3096.07   238.43096.132
   268.4 3096.17   293.3 3094.43     308 3097.28   354.6 3095.35   395.9 3096.87
   438.4 3096.73   462.8 3098.14   602.7 3095.29   608.3 3096.44   614.9 3099.53
   625.3 3107.91   636.3 3115.19   676.3 3128.64     706  3141.1   746.7 3154.14
#Mann= 5 ,-1,0
       0      .1       0   222.4    .045       0   238.4      .1       0
  567.11     .06       0  627.11      .1       0
#XS Ineff= 2 , 0
                          310.75         3100.09
Permanent Ineff=
       F       F
Bank Sta=222.4,238.4
XS Rating Curve= 0 ,0
Exp/Cntr(USF)=0,0
Exp/Cntr=0.3,0.1