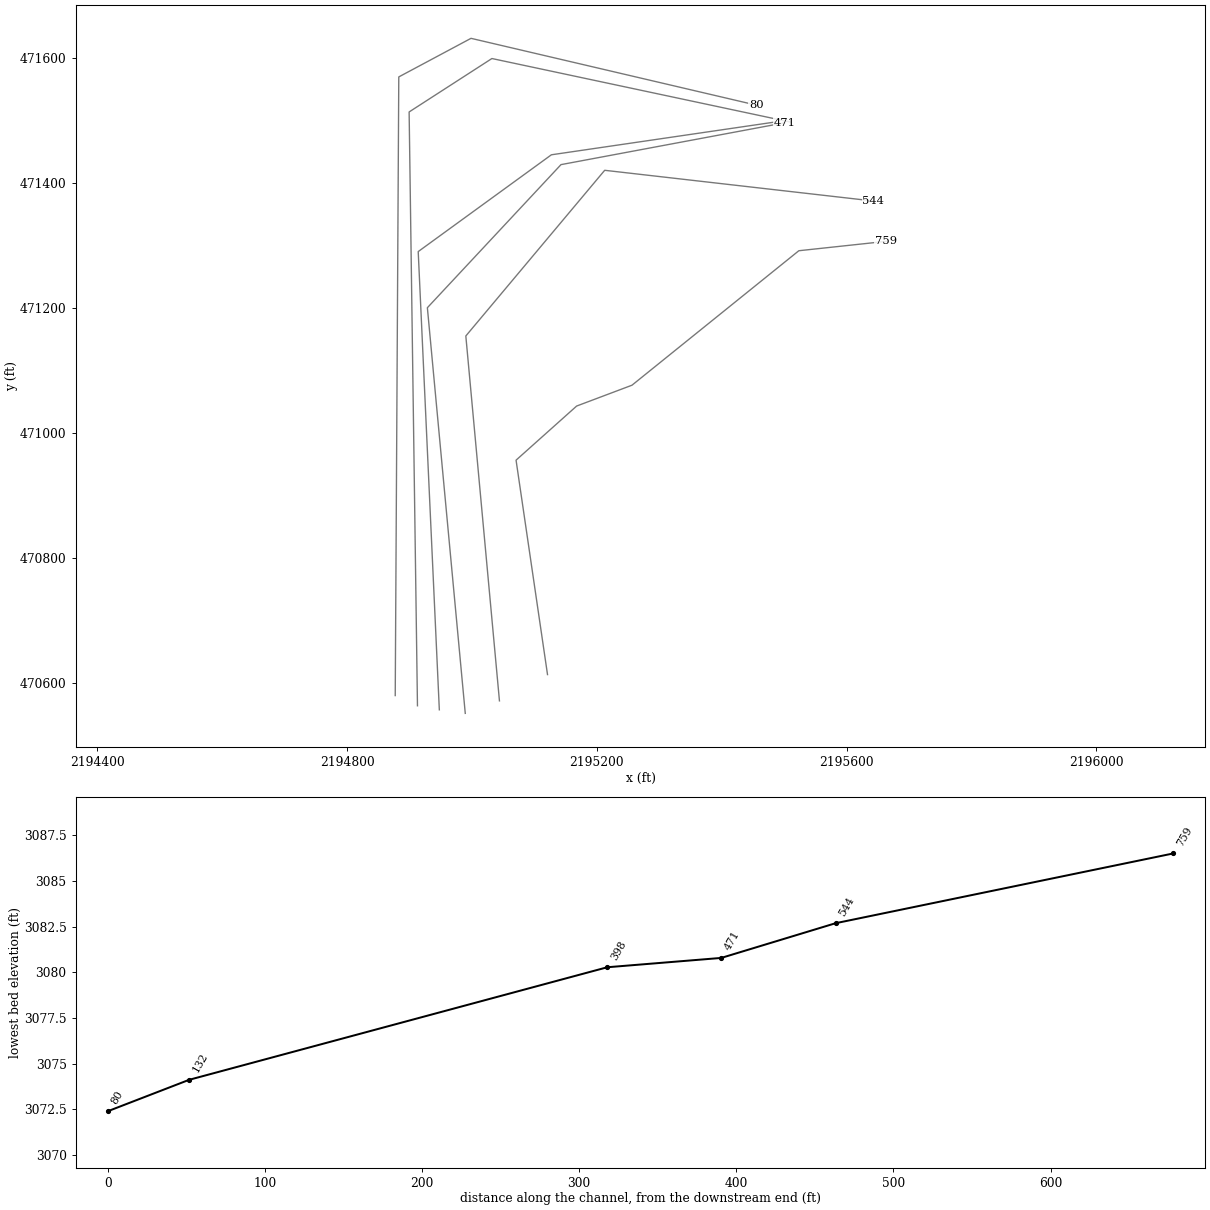
HEC-RAS study DAYRN.prj: DAYRN

--- DAYRN.g01 (geometry) --- (continued)

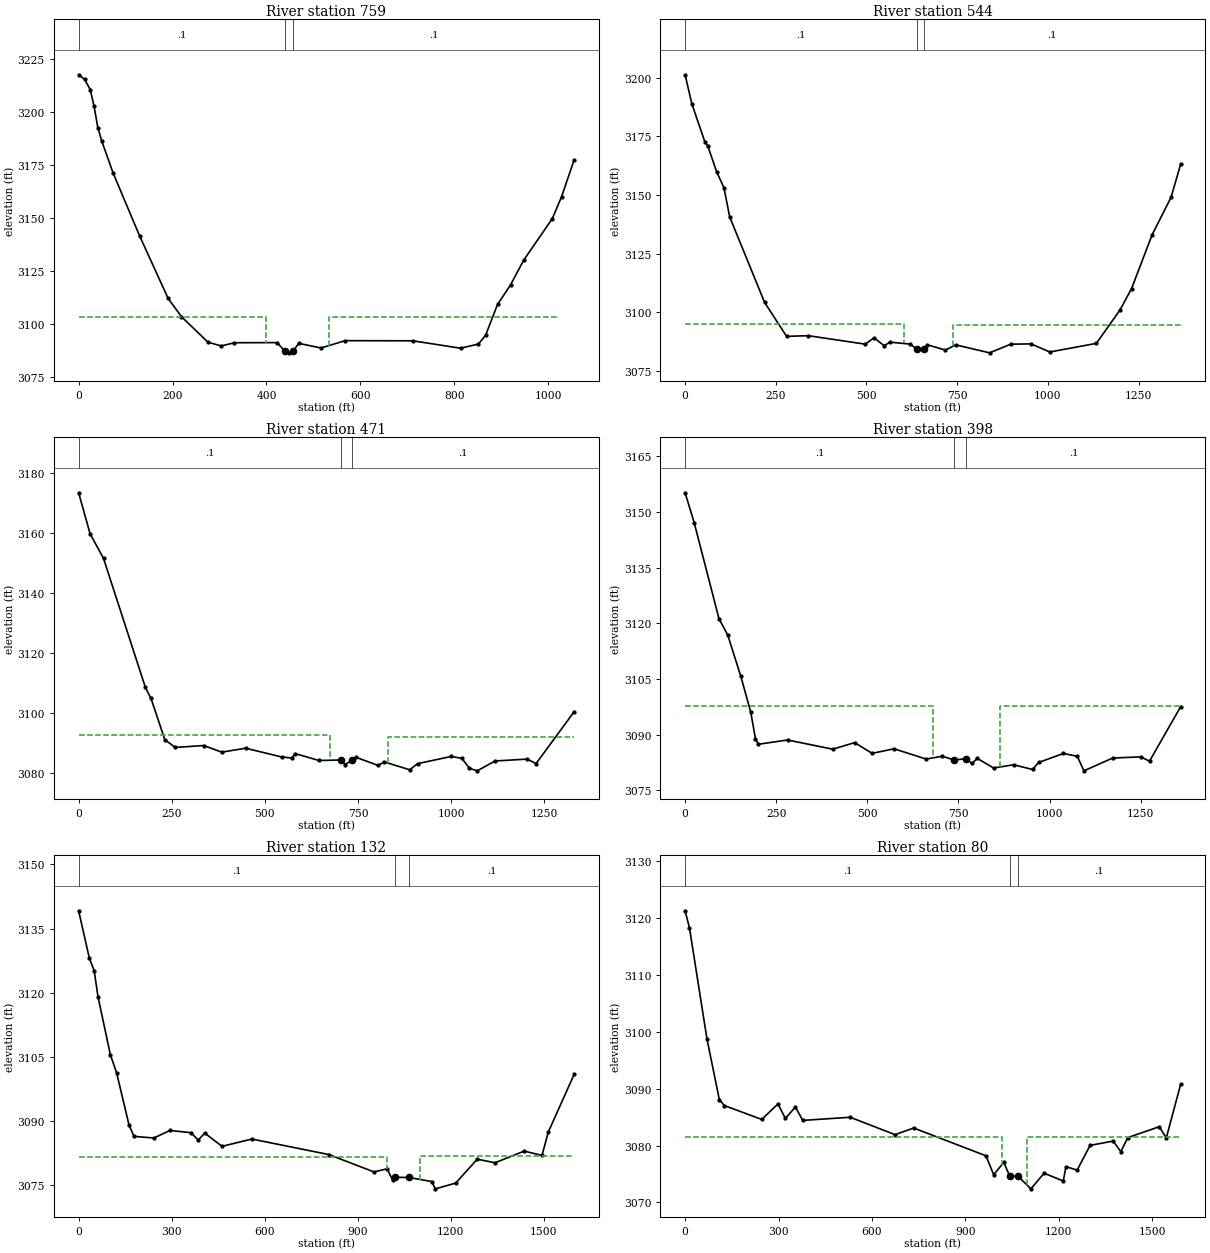
Type RM Length L Ch R = 1 ,759     ,211.8,215,216.2
XS GIS Cut Line= 6
2195120.86478344470612.7597214012195070.47676331470956.155270847
2195167.49571979471042.8353847762195256.14826569471076.216421257
2195523.37378949471291.583655043 2195662.9083836471306.575493126
#Sta/Elev= 30
       0 3217.77    12.6 3215.63    24.7 3210.76    32.8 3202.98    40.9 3192.85
    48.9 3186.71    73.2 3171.52   129.8 3141.74   190.4 3112.31   218.7 3103.64
   275.3 3091.57   303.6 3089.76   331.9 3091.28   422.7 3091.34   438.7 3087.42
   448.2 3086.51   457.4 3087.46   468.7 3090.99   516.4 3088.81   567.7 3092.26
     712 3092.19   813.4 3088.69   851.4 3090.65   866.7 3094.78   892.2 3109.36
   919.9  3118.6   948.1 3130.32  1008.9  3149.9  1028.6 3160.23  1055.4 3177.63
#Mann= 3 ,-1,0
       0      .1       0   438.7    .045       0   457.4      .1       0
#XS Ineff= 2 ,-1
       0     400 3103.36  532.28 1021.073103.371
Permanent Ineff=
       F       F
Bank Sta=438.7,457.4
XS Rating Curve= 0 ,0
Exp/Cntr(USF)=0,0
Exp/Cntr=0.3,0.1

Type RM Length L Ch R = 1 ,544     ,73.8,72.8,71.8
XS GIS Cut Line= 4
2195043.88358195470570.6695077032194990.02454908471155.052675596
 2195212.4240642 471420.394439062195642.55341995471371.236798403
#Sta/Elev= 30
       0 3201.27    18.6 3188.89    54.7 3172.56    62.8 3170.81    86.9 3159.91
     107 3153.15     123 3140.63     219 3104.25   279.7 3089.72   339.9    3090
   496.6 3086.39   520.7 3089.09   548.8 3085.74   564.8 3087.25   621.3  3086.4
     6383084.283   657.93084.215   667.9 3086.11   717.7 3083.87   745.9 3086.09
   839.3 3082.69   897.6 3086.38   953.8  3086.5  1005.3 3083.05  1133.7 3086.73
  1198.5 3100.89  1230.8 3110.12  1287.1 3132.93  1339.5 3148.98    1366 3163.13
#Mann= 3 ,-1,0
       0      .1       0     638    .045       0   657.9      .1       0
#XS Ineff= 2 , 0
          602.81 3094.86  739.68         3094.56
Permanent Ineff=
       F       F
Bank Sta=638,657.9
XS Rating Curve= 0 ,0
Exp/Cntr(USF)=0,0
Exp/Cntr=0.3,0.1

Type RM Length L Ch R = 1 ,471     ,69.3,72.5,71.1
XS GIS Cut Line= 4
2194989.13274161470550.637552876 2194928.4528645471200.324770712
2195142.43593222471429.4827834592195500.68748098471496.502153646
#Sta/Elev= 30
       0 3173.27    30.7 3159.67    66.8 3151.44   179.3 3108.51   194.3 3104.88
   231.5 3091.12   259.7 3088.57     336 3089.21   384.2    3087   448.5 3088.32
   544.9  3085.4     573 3085.07   581.1 3086.54   645.3 3084.23  705.49  3084.4
   715.2 3082.87  733.56 3084.25   745.9 3085.24   804.5 3082.57   819.9 3083.77
     889 3081.14     910 3083.18  1000.4 3085.57  1028.9 3084.95  1049.2 3081.64
  1070.1 3080.79  1118.4 3084.07  1203.8 3084.69  1228.3 3083.22  1330.5 3100.47
#Mann= 3 ,-1,0
       0      .1       0  705.49    .045       0  733.56      .1       0
#XS Ineff= 2 , 0
          675.51 3092.66   830.2         3092.19
Permanent Ineff=
       F       F
Bank Sta=705.49,733.56
XS Rating Curve= 0 ,0
Exp/Cntr(USF)=0,0
Exp/Cntr=0.3,0.1

Type RM Length L Ch R = 1 ,398     ,273.3,266.1,274.6
XS GIS Cut Line= 4
2194947.60567338470556.340659644 2194913.7746645471290.213313739
 2195127.0572993471445.2236001692195484.77093822471497.644232298
#Sta/Elev= 30
       0 3155.18    24.9 3147.15    92.9 3121.28     117 3116.85     153 3105.71
   180.2 3096.06     193 3088.95   201.1 3087.44   281.1 3088.59   405.3 3086.11
   465.3 3087.88   513.2 3084.99   573.4 3086.22   661.5 3083.45   705.6 3084.22
   738.43083.197   771.43083.556   787.1 3082.26   801.9 3083.63   846.4 3081.05
   901.7 3081.92   953.3 3080.65     970 3082.53    1038 3084.96  1076.3  3084.2
  1094.4 3080.28  1173.3 3083.73  1250.1 3084.04  1274.4 3082.88  1359.8 3097.56
#Mann= 3 ,-1,0
       0      .1       0   738.4    .045       0   771.4      .1       0
#XS Ineff= 2 , 0
          680.88 3097.69  864.97         3097.62
Permanent Ineff=
       F       F
Bank Sta=738.4,771.4
XS Rating Curve= 0 ,0
Exp/Cntr(USF)=0,0
Exp/Cntr=0.3,0.1

Type RM Length L Ch R = 1 ,132     ,52.7,51.8,52.9
XS GIS Cut Line= 4
2194912.58085516 470562.811945032194899.22868708471513.846490121
2195031.79788353471599.399866905 2195509.6635917471497.660716135
#Sta/Elev= 30
       0 3139.15    34.3 3128.14    50.1 3125.13    62.4 3119.07   102.4 3105.46
   122.4 3101.26   162.4 3089.06   178.4 3086.39   242.4 3086.01   294.4 3087.77
   362.4 3087.25   385.4 3085.52   406.4 3087.15   462.4 3084.06   558.4 3085.77
   806.4 3082.14   952.3 3078.07   994.2 3078.81  1012.1  3076.2  1021.4 3076.81
  1063.9 3076.78  1137.9 3075.83  1150.2 3074.12  1215.6 3075.47  1285.1 3081.05
  1342.4 3080.22  1436.5 3082.95  1493.7 3081.93  1514.2 3087.42  1597.5  3100.9
#Mann= 3 ,-1,0
       0      .1       0  1021.4    .045       0  1063.9      .1       0
#XS Ineff= 2 , 0
          993.21 3081.61 1101.75         3081.76
Permanent Ineff=
       F       F
Bank Sta=1021.4,1063.9
XS Rating Curve= 0 ,0
Exp/Cntr(USF)=0,0
Exp/Cntr=0.3,0.1

Type RM Length L Ch R = 1 ,80      ,,,
XS GIS Cut Line= 4
2194876.97745604470579.142454958 2194882.6541883471569.942193889
2194998.33708957471631.737606926 2195455.0950273471524.797409658
#Sta/Elev= 30
       0 3121.31      14 3118.32      70 3098.82     110 3088.09     126 3087.05
     246 3084.61     298 3087.33     322 3084.79     354 3086.79     378 3084.44
   530.2 3084.99     674 3081.93     734  3083.1   966.1 3078.21   990.8 3074.88
  1023.2 3077.06 1042.67 3074.59  1068.2 3074.66  1110.4  3072.4  1152.6 3075.15
  1214.2 3073.78  1222.9 3076.31  1258.8 3075.69  1300.5 3080.05  1374.5  3080.8
  1399.1 3078.94  1421.4 3081.41  1522.3 3083.33  1545.1 3081.36  1591.1 3090.79
#Mann= 3 ,0,0
       0      .1       0 1042.67    .045       0  1068.2      .1       0
#XS Ineff= 2 , 0
          1016.9 3081.52 1097.86         3081.44
Permanent Ineff=
       F       F
Bank Sta=1042.67,1068.2
XS Rating Curve= 0 ,0
Exp/Cntr(USF)=0,0
Exp/Cntr=0.3,0.1
LCMann Table=0

Chan Stop Cuts=-1
Use User Specified Reach Order=0
Composite Channel Slope=5